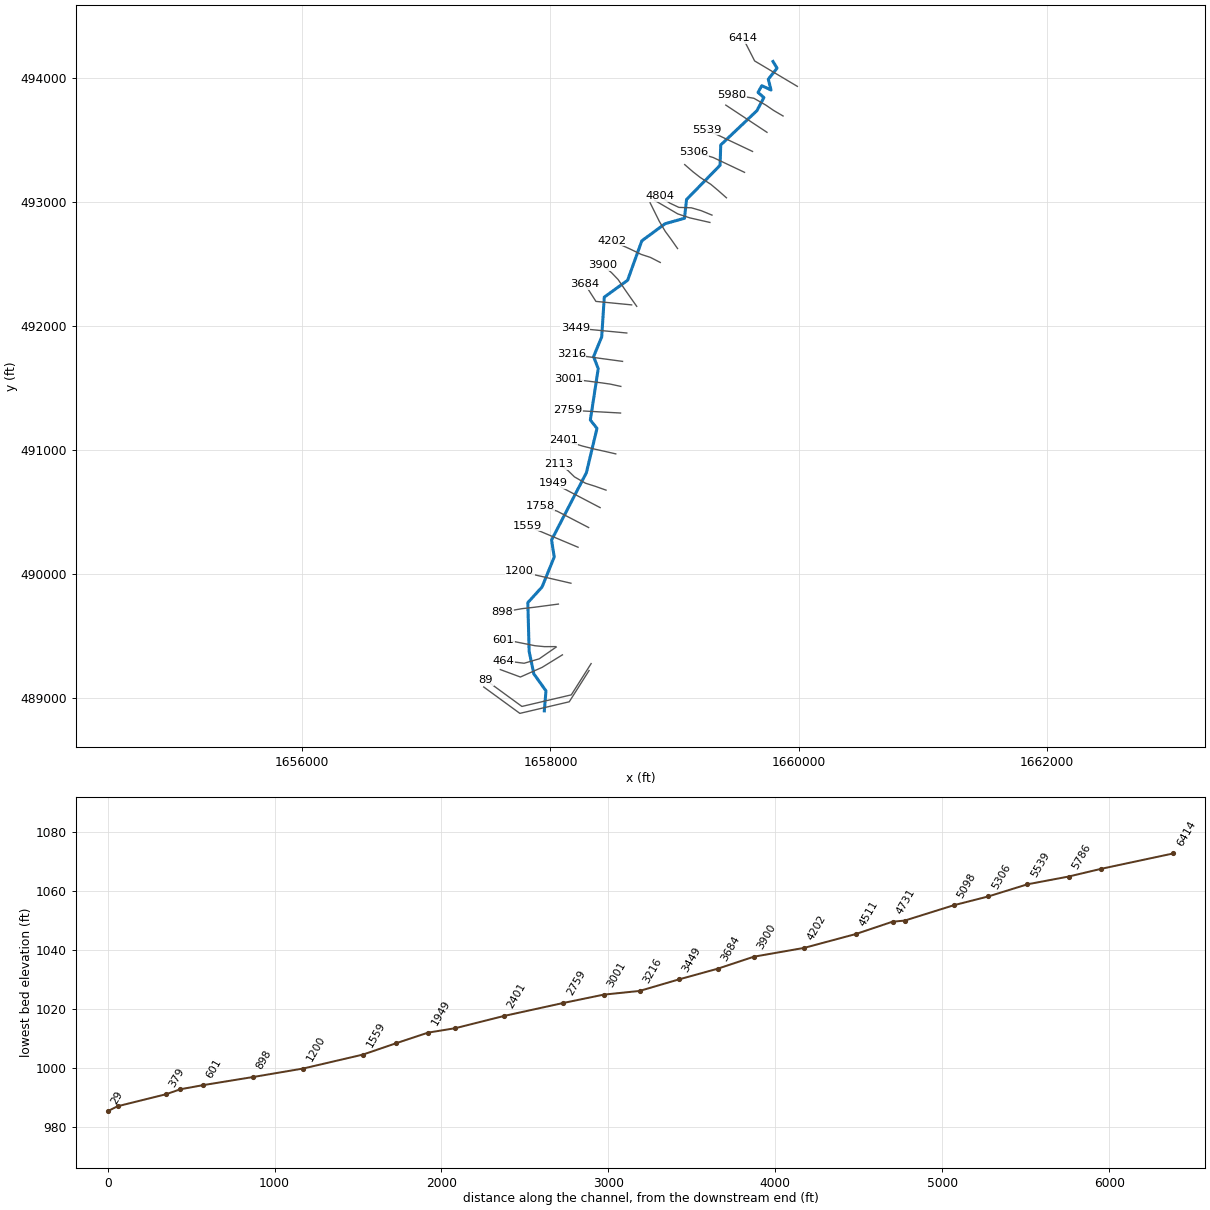
--- StraightRn.prj (project) ---

Proj Title=StraightRn
Current Plan=p01
Default Exp/Contr=0,0
English Units
Geom File=g01
Flow File=f01
Plan File=p01
BEGIN DESCRIPTION:
END DESCRIPTION:
DSS Export Rating Curves= 0
DSS Export Rating Curve Sorted= 0
DSS Export Volume Flow Curves= 0
DXF OffsetX= 0
DXF OffsetY= 0
DXF ScaleX= 0
DXF ScaleY= 0

--- StraightRn.p01 (plan) ---

Plan Title=Floodplain
Program Version=6.60
Short Identifier=Floodplain
Geom File=g01
Flow File=f01
Subcritical Flow
K Sum by GR= 0
Std Step Tol= 0.01
Critical Tol= 0.01
Num of Std Step Trials= 20
Max Error Tol= 0.3
Flow Tol Ratio= 0.001
Split Flow NTrial= 30
Split Flow Tol= 0.02
Split Flow Ratio= 0.02
Log Output Level= 0
Friction Slope Method= 1
Unsteady Friction Slope Method= 2
Unsteady Bridges Friction Slope Method= 1
Parabolic Critical Depth
Global Vel Dist= 0 , 0 , 0
Global Log Level= 0
CheckData=False
Encroach Param=-1 ,0,0, 0
Flow Ratio Tolerance=0.1
Flow Ratio Min Ratio=0.5
Flow Ratio Max Ratio=4
Flow Ratio Max Iterations= 10
Mapping Interval=1HOUR
Computation Time Step Use Courant=        0
Computation Time Step Use Time Series=    0
Computation Time Step Count To Double=0
Computation Time Step Max Doubling=0
Computation Time Step Max Halving=0
Computation Time Step Residence Courant=0
Run HTab= 0
Run UNet= 0
Run Sediment= 0
Run PostProcess= 0
Run WQNet= 0
Run RASMapper=-1
UNET Theta= 0
UNET Theta Warmup= 0
UNET ZTol= 0
UNET ZSATol= 0
UNET MxIter= 0
UNET Max Iter WO Improvement= 0
UNET MaxInSteps= 0
UNET DtIC= 0
UNET DtMin= 0
UNET MaxCRTS= 0
UNET WFStab= 0
UNET SFStab= 0
UNET WFX= 1
UNET SFX= 1
UNET Gravity=32.17405
UNET 1D Methodology=Finite Difference
UNET DSS MLevel= 1
UNET Pardiso=0
UNET DZMax Abort= 0
UNET Use Existing IB Tables= 0
UNET Froude Reduction=False
UNET Froude Limit= 0
UNET Froude Power= 0
UNET D1 Cores= 0
UNET WindReference=Eulerian
UNET WindDragFormulation=Hsu (1988)
UNET D2 Coriolis=0
UNET D2 Cores= 0
UNET D2 Theta= 1
UNET D2 Theta Warmup= 1
UNET D2 Z Tol= 0.01
UNET D2 Volume Tol= 0.01
UNET D2 Max Iterations= 20
UNET D2 Advanced Convergence=0
UNET D2 WS Max Tol=0.15
UNET D2 WS RMS Tol=0.002
UNET D2 WS Stall Tol=1
UNET D2 Equation= 0
UNET D2 RampUpFraction=0.1
UNET D2 TimeSlices= 1
UNET D2 Turbulence Formulation=Non-Conservative (original)
UNET D2 Eddy Viscosity=0.3
UNET D2 Transverse Eddy Viscosity=0.1
UNET D2 Smagorinsky Mixing=0
UNET D2 BCVolumeCheck=0
UNET D2 Cores=0
UNET D2 SolverType=PARDISO (Direct)
UNET D2 Minimum Iterations= 3
UNET D2 Maximum Iterations= 30
UNET D2 Restart Number= 10
UNET D2 Relaxation Coeff=1.3
UNET D2 SOR Precondition Iterations= 10
UNET D2 ILUT Maximum Fill= 8
UNET D2 ILUT Tolerance=1E-08
UNET D2 Convergence Tolerance=0.00001
PS Theta= 1
PS WS Tol= 0.01
PS Volume Tol= 0.01
PS Max Iterations= 20
PS Equation= 0
PS Advance Time Step=-1
PS Target Courant=0.9
PS Time Slices= 1
PS Iterate With 2D=0
PS Project Initial WSE from DS=-1
PS Ramp Up Initial WSE from US=-1
PS Cores=0
UNET D1D2 MaxIter= 0
UNET D1D2 ZTol=0.01
UNET D1D2 QTol=0.1
UNET D1D2 MinQTol=1
Write IC File= 0
Write IC File at Fixed DateTime=0
Write IC File at Sim End=0
Echo Input=False
Echo Parameters=False
Echo Output=False
Write Detailed= 0
HDF Write Warmup=0
HDF Write Time Slices=0
HDF Flush=0
HDF Compression= 1
HDF Chunk Size= 1
HDF Spatial Parts= 1
HDF Use Max Rows=0
HDF Fixed Rows= 1
Calibration Method= 0
Calibration Iterations= 20
Calibration Max Change=0.05
Calibration Tolerance=0.2
Calibration Maximum=1.5
Calibration Minimum=0.5
Calibration Optimization Method= 1
WQ AD Non Conservative
WQ ULTIMATE=-1
WQ Max Comp Step=1HOUR
WQ Output Interval=15MIN
WQ Output Selected Increments= 0
WQ Create Restart=0
WQ Fixed Restart=0
WQ System Summary=0
WQ Write To DSS=0
Sorting and Armoring Iterations= 10
XS Update Threshold= 0.02
Bed Roughness Predictor= 0
Processes Affected by Predictor=Sediment Only
Hydraulics Update Threshold= 0.02
Energy Slope Method= 1
Volume Change Method= 1
Sediment Retention Method= 0
Sediment TS Multiplier= 1
Warm Up Method= 0
XS Weighting Method= 0
Number of US Weighted Cross Sections= 1
Number of DS Weighted Cross Sections= 1
Upstream XS Weight=0
Main XS Weight=1
Downstream XS Weight=0
Number of DS XS's Weighted with US Boundary= 1
Upstream Boundary Weight= 1
Weight of XSs Associated with US Boundary= 0
Number of US XS's Weighted with DS Boundary= 1
Downstream Boundary Weight= 0.5
Weight of XSs Associated with DS Boundary= 0.5
Percentile Method= 0
Sediment Output Level= 3
Mass or Volume Output= 0
Output Increment Type= 1
Profile and TS Output Increment= 1
Transport Output Increment 1
XS Output Flag= 0
XS Output Increment= 10
Read HDF5 Sediment Hotstart= 0
Sediment Hotstart Type= 0
Write Gradation File= 0
Read Gradation Hotstart= 0
Write HDF5 File= 1
Write Binary Output= 1
Write DSS Sediment File= 0
DSS Sediment Output Type= 1
SV Curve= 0
Specific Gage Flag= 0
Subcell Erosion Methods= 0
Subcell Deposition Methods= 0
Advection Scheme= 1
Matrix Solver= 0
Implicit Weighting Factor= 1
Maximum Outer Loop Convergence Iterations= 5
Convergence Maximum Absolute= 0.001
Convergence RMSE= 0.0001
Grain Fractions Max Abs Error= 0.001
Max Subgrid Regions= 1
Max Subgrid Length Scale= 3.402823E+38
Initial Layer Thickness= 3
Min Layer Thickness= 0.1
Max Layer Thickness= 6
Number of Layers= 5

--- StraightRn.f01 (steady flow) ---

Flow Title=Flow
Program Version=6.60
Number of Profiles= 1
Profile Names=P100yr
River Rch & RM=StraightRn,Main            ,6414
     754
River Rch & RM=StraightRn,Main            ,3900
     845
Boundary for River Rch & Prof#=StraightRn,Main            , 1
Up Type= 0
Dn Type= 3
Dn Slope=0.012317
DSS Import GetInterval= 0
DSS Import GetPeak= 0
DSS Import FillOption= 0

--- StraightRn.g01 (geometry) ---

Geom Title=Geometry
Program Version=6.60

River Reach=StraightRn      ,Main
Reach XY= 30
     1659793.795      494131.758     1659826.408      494077.805
     1659755.922      493988.787     1659777.761      493901.901
     1659703.556      493936.655     1659672.655      493881.964
     1659720.304       493841.25     1659664.216      493735.471
     1659372.391      493458.747     1659367.125      493295.101
     1659096.853      493019.248     1659080.327      492868.196
     1658923.463      492823.814     1658736.213       492685.98
     1658621.711      492368.016     1658433.851      492232.521
     1658412.951      491911.748     1658347.566      491752.987
     1658384.904      491656.233     1658321.583      491241.922
     1658374.935      491174.342     1658289.556      490816.936
     1658008.873      490274.713     1658030.406      490138.128
     1657932.242       489895.99     1657817.559      489769.838
     1657828.156      489376.939     1657865.928      489195.887
     1657963.876       489058.67     1657950.605      488897.774

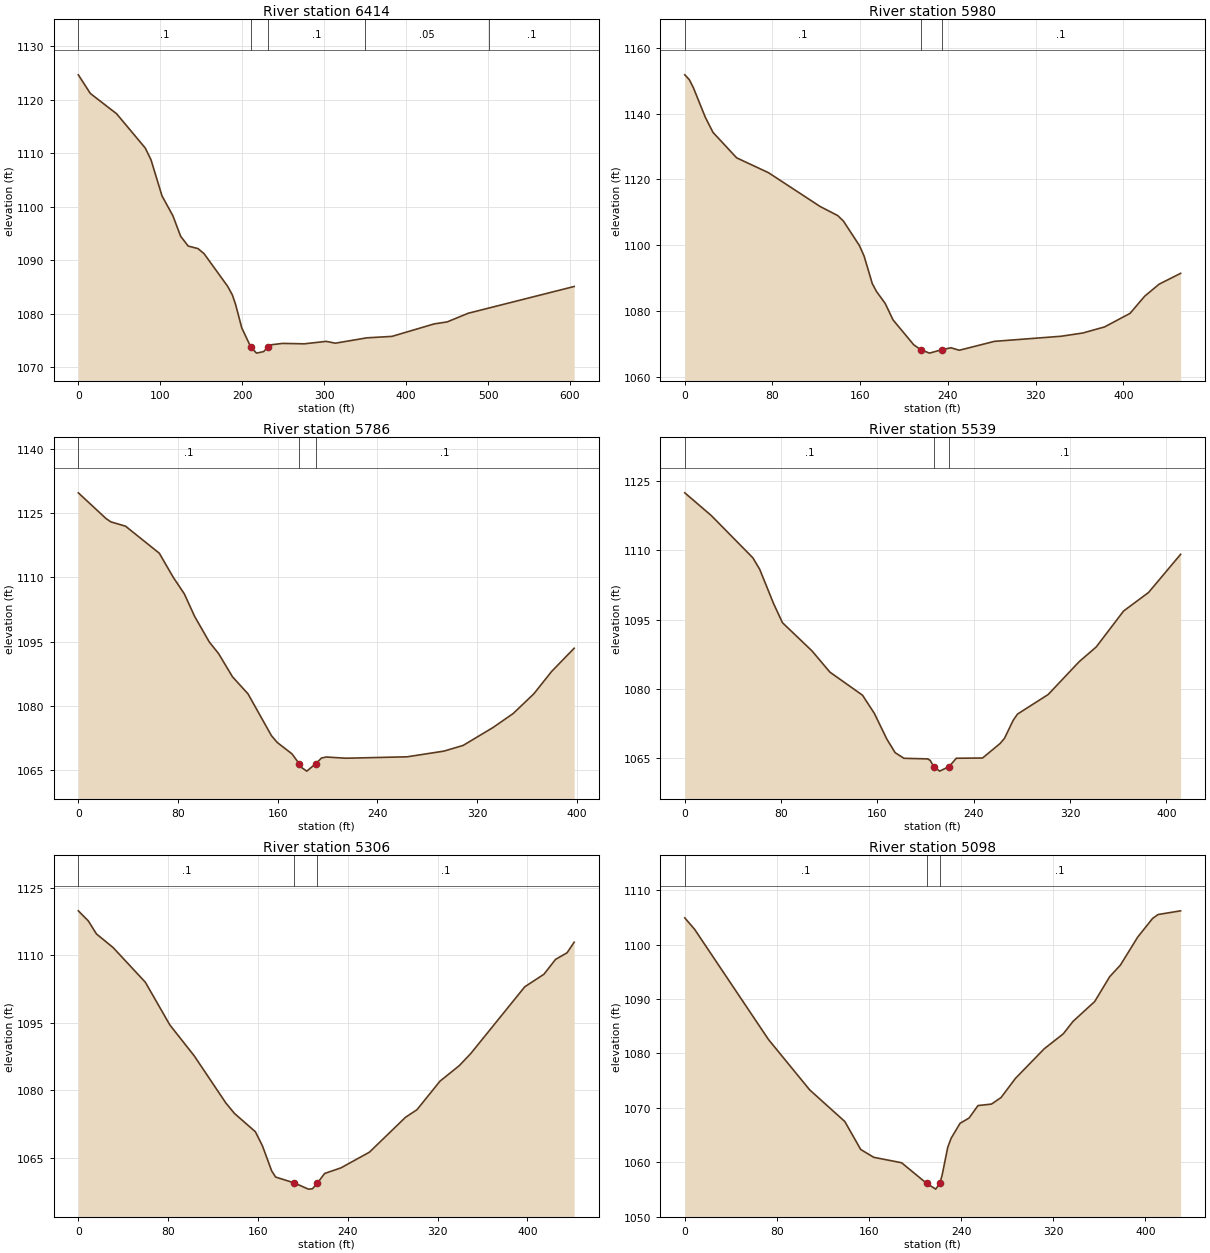
Type RM Length L Ch R = 1 ,6414    ,420.8,434.1,417.7
XS GIS Cut Line= 3
1659990.04747305 493931.125483251659645.67252032494136.157969559
1659553.10931048494318.298479242
#Sta/Elev= 30
       0 1124.65    14.7 1121.16    46.7 1117.37    81.7 1110.96    88.7 1108.76
   102.1 1102.02   115.5 1098.27   124.8 1094.48   134.1 1092.63     146 1092.16
   153.4 1091.22   182.3 1085.09     188 1083.48   191.8 1081.78   199.5 1077.32
  210.741073.667   217.5 1072.61   226.2  1072.9  230.871073.666   234.9 1074.16
   249.1 1074.43   275.8 1074.35   302.5 1074.81   313.7 1074.47   352.2 1075.47
   382.7 1075.74   434.2 1078.07   450.2 1078.45   475.9 1080.07   605.1 1085.07
#Mann= 5 ,-1,0
       0      .1       0  210.74    .045       0  230.87      .1       0
     350     .05       0  500.79      .1       0
Bank Sta=210.74,230.87
XS Rating Curve= 0 ,0
Exp/Cntr(USF)=0,0
Exp/Cntr=0.3,0.1

Type RM Length L Ch R = 1 ,5980    ,192.6,193.7,190
XS GIS Cut Line= 6
1659874.68963292493692.4453275051659797.73210968493737.680801332
1659734.47337793493781.047512501  1659639.820352493835.107771844
1659556.65746059493849.384646177  1659464.682907 493862.71434392
#Sta/Elev= 30
       0 1151.72     4.1 1150.27     7.9 1147.77    18.6 1138.95    25.7 1134.29
    47.3 1126.56    76.4 1122.05   123.5 1111.81   139.5 1109.07   144.7  1107.4
   159.3 1099.98   163.6 1096.76     171 1088.48   174.8  1086.1   182.8 1082.44
     190 1077.44   208.8 1069.92  215.391068.407   223.2 1067.38  234.41 1068.41
   242.8    1069   250.4 1068.25   282.5 1070.95   343.2 1072.49   363.1 1073.48
     383 1075.33   406.2 1079.44   419.5 1084.63   432.7 1088.28   452.3 1091.56
#Mann= 3 ,-1,0
       0      .1       0  215.39    .045       0  234.41      .1       0
Bank Sta=215.39,234.41
XS Rating Curve= 0 ,0
Exp/Cntr(USF)=0,0
Exp/Cntr=0.3,0.1

Type RM Length L Ch R = 1 ,5786    ,244.8,246.6,246.1
XS GIS Cut Line= 2
1659745.29012641493560.7401548361659413.23550335493780.145283341
#Sta/Elev= 30
       0 1129.71    22.2 1123.72    26.1 1122.94    37.9 1121.93      65 1115.62
    76.2    1110    85.1 1106.13    93.4 1100.86   105.2 1094.88   112.6  1092.2
   123.8 1086.77   136.2 1082.81     155 1073.06   159.7 1071.46   171.5 1068.81
  177.241066.523   179.4 1065.58   183.4 1064.78  190.661066.522   195.2 1067.84
   199.1 1068.07   214.8 1067.79   263.9 1068.12   293.5 1069.45   308.9 1070.78
   332.8 1074.94   349.1 1078.23   365.7 1082.84   379.9 1088.03     398 1093.45
#Mann= 3 ,-1,0
       0      .1       0  177.24    .045       0  190.66      .1       0
Bank Sta=177.24,190.66
XS Rating Curve= 0 ,0
Exp/Cntr(USF)=0,0
Exp/Cntr=0.3,0.1

Type RM Length L Ch R = 1 ,5539    ,230.6,233.7,229.9
XS GIS Cut Line= 2
1659628.82553046493406.6444853631659256.58208444493582.813175056
#Sta/Elev= 30
       0 1122.45      22 1117.53    56.5 1108.38    62.2 1105.89    73.7 1098.48
    81.1 1094.32   105.7 1088.19   120.5 1083.61   147.6 1078.61   157.5 1074.64
   167.8  1069.1   174.7 1066.16     182 1064.94   201.8 1064.81   203.8 1064.48
   206.81063.146   211.7 1062.16  219.521063.146   225.5 1064.95   247.3    1065
   261.8 1068.13   265.5 1069.26   272.7 1073.15   276.3 1074.51   301.8 1078.76
   327.5 1085.86   341.7 1089.06   364.4 1096.84   385.2 1100.87   411.8 1109.13
#Mann= 3 ,-1,0
       0      .1       0   206.8    .045       0  219.52      .1       0
Bank Sta=206.8,219.52
XS Rating Curve= 0 ,0
Exp/Cntr(USF)=0,0
Exp/Cntr=0.3,0.1

Type RM Length L Ch R = 1 ,5306    ,209.6,207.9,205.9
XS GIS Cut Line= 3
1659564.20974143493238.1677911781659311.36741367493357.848401491
1659156.45320851493404.753645673
#Sta/Elev= 30
       0 1119.85     8.9 1117.61    16.1 1114.73      31 1111.69    59.7 1103.99
    81.5 1094.52   103.2 1087.66   131.4 1077.18     139 1074.88   157.7  1070.8
     164 1067.66   172.2  1062.1   175.8 1060.73  192.381059.437   204.9 1058.06
   208.5 1058.13  212.981059.436   219.4 1061.54   233.9 1062.78   259.3 1066.27
   291.3 1073.99   301.6 1075.69   322.1 1082.03   339.3 1085.48   349.6 1088.19
   397.6 1102.98   414.7 1105.77     425 1109.06   435.3 1110.54   441.6 1112.88
#Mann= 3 ,-1,0
       0      .1       0  192.38    .045       0  212.98      .1       0
Bank Sta=192.38,212.98
XS Rating Curve= 0 ,0
Exp/Cntr(USF)=0,0
Exp/Cntr=0.3,0.1

Type RM Length L Ch R = 1 ,5098    ,288.2,293.8,297.7
XS GIS Cut Line= 6
1659418.42348509493032.9906096761659351.39671625493092.168969005
1659292.34499709 493141.673791261659207.59155767493196.610361174
1659148.25932726493242.9665676651659081.90020801 493300.66756776
#Sta/Elev= 30
       0 1104.92     8.5 1102.83    72.7 1082.57   108.5 1073.31     139  1067.5
   152.8 1062.36   164.1 1060.92   188.3 1059.92  209.981056.149     218 1055.07
  221.471056.147   223.5  1057.6   228.4 1062.75   231.3  1064.4   239.1 1067.17
   246.9 1068.13   254.7 1070.43   266.4  1070.7   274.7  1071.9   287.2 1075.42
   312.2 1080.86   328.8 1083.62   337.2 1085.89   356.1 1089.56   369.1 1094.12
   378.4 1096.25   393.4 1101.39   406.3 1104.81   411.1 1105.54   430.7 1106.22
#Mann= 3 ,-1,0
       0      .1       0  209.98    .045       0  221.47      .1       0
Bank Sta=209.98,221.47
XS Rating Curve= 0 ,0
Exp/Cntr(USF)=0,0
Exp/Cntr=0.3,0.1

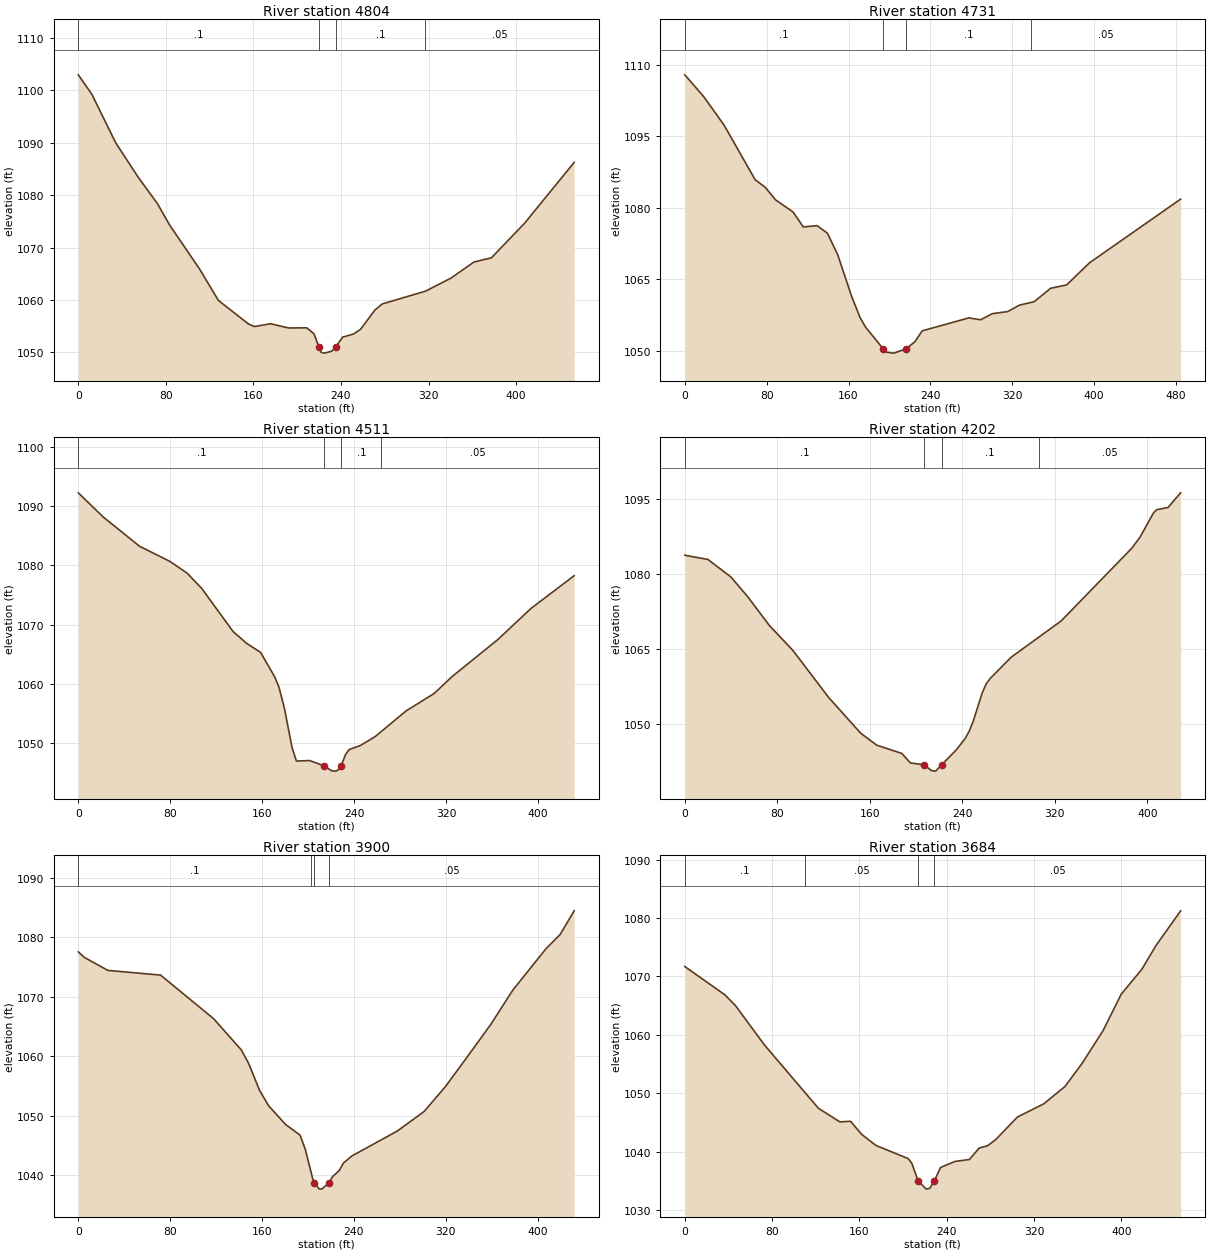
Type RM Length L Ch R = 1 ,4804    ,76.1,73.1,68.9
XS GIS Cut Line= 6
1659301.80232726492893.5834081771659214.46785626492929.434058249
1659135.36040293  492952.4153115 1659035.4065346492955.626919255
 1658962.2882425 492989.969698341658884.06530184493044.835730344
#Sta/Elev= 30
       0 1102.95    12.3 1099.26    34.2 1089.97    54.8  1083.4    72.5 1078.32
    83.2 1074.38   110.9 1065.89     128 1059.93   155.5 1055.44   160.8 1054.95
   175.8 1055.48   192.3 1054.67   208.7 1054.71   215.3 1053.57   219.81051.096
   221.8 1050.04   225.1 1049.88   231.7 1050.27  235.331051.097   241.5 1052.92
   251.4 1053.52   257.9 1054.42   271.1 1058.11   277.7 1059.26   317.3  1061.7
   340.5 1064.18   361.5 1067.25   377.5 1068.06   407.8 1074.65   453.1 1086.25
#Mann= 4 ,-1,0
       0      .1       0   219.8    .045       0  235.33      .1       0
  316.79     .05       0
Bank Sta=219.8,235.33
XS Rating Curve= 0 ,0
Exp/Cntr(USF)=0,0
Exp/Cntr=0.3,0.1

Type RM Length L Ch R = 1 ,4731    ,226,220.3,208.3
XS GIS Cut Line= 4
1659285.22752736492834.3181039461659122.76681635492871.253333975
1659025.79885801492903.3287383451658839.62200865493012.443616067
#Sta/Elev= 30
       0 1107.94    18.2 1103.44    38.4 1097.38    68.7 1085.93    78.5 1084.33
    88.8 1081.67   105.7 1079.15   115.8    1076   129.2 1076.27   139.3  1074.7
   149.4 1070.18   162.9  1061.5   171.3 1056.95   176.6 1054.98  193.911050.397
   197.3 1049.69   204.2  1049.5  216.311050.397     225 1051.93   231.9 1054.17
   277.6  1056.9     289  1056.5   300.4 1057.78   315.6 1058.23     327 1059.58
   341.4  1060.3   357.5 1063.12   373.1 1063.82   395.5 1068.47   484.5 1081.84
#Mann= 4 ,-1,0
       0      .1       0  193.91    .045       0  216.31      .1       0
  338.74     .05       0
Bank Sta=193.91,216.31
XS Rating Curve= 0 ,0
Exp/Cntr(USF)=0,0
Exp/Cntr=0.3,0.1

Type RM Length L Ch R = 1 ,4511    ,303,308.7,312
XS GIS Cut Line= 5
1659024.38621542492624.0672149211658972.25213334492698.477499172
1658925.54914276492761.9317685961658877.55356739492842.899298569
1658803.04178232492993.214671098
#Sta/Elev= 30
       0  1092.2    21.7 1088.12    53.3  1083.2    79.5 1080.67    94.7 1078.67
   107.5 1076.07   134.6 1068.85   146.3 1066.87   158.6 1065.32   170.8 1061.24
   174.6 1059.46   179.4 1055.87     186 1049.28   189.8 1047.02   201.3  1047.1
  214.021046.206   220.3 1045.39   224.1 1045.32   227.3 1045.68  228.711046.205
   232.5  1048.1   235.6 1048.94   245.4 1049.63   258.3 1051.13   285.2 1055.46
   309.7  1058.4   325.2 1061.24   364.9 1067.45   394.2 1072.77   431.5 1078.24
#Mann= 4 ,-1,0
       0      .1       0  214.02    .045       0  228.71      .1       0
  263.77     .05       0
Bank Sta=214.02,228.71
XS Rating Curve= 0 ,0
Exp/Cntr(USF)=0,0
Exp/Cntr=0.3,0.1

Type RM Length L Ch R = 1 ,4202    ,304.7,302,298.7
XS GIS Cut Line= 6
1658885.02232093492511.8095654251658804.51887301 492553.04307875
1658732.60661526 492576.303859011658642.41847542492619.914992258
1658574.05411084 492650.889339761658493.91942859492686.155345336
#Sta/Elev= 30
       0 1083.73      20 1082.89    39.8 1079.41    54.2 1075.52      73 1069.75
    93.5 1064.73   124.5 1055.32   152.1 1048.22     166 1045.82   187.7 1044.17
   195.1 1042.28  206.83 1041.89   213.3 1040.76   216.9 1040.64   222.1 1041.89
   235.1 1044.96   242.4 1047.15   246.1 1048.67   249.7 1050.78     257 1056.13
   260.6 1058.05   264.3 1059.18   282.3 1063.39   325.5 1070.62   386.6 1085.14
   393.7 1087.33   405.4 1092.21   408.1 1092.82   417.9 1093.27   428.8 1096.19
#Mann= 4 ,-1,0
       0      .1       0  206.83    .045       0   222.1      .1       0
  306.21     .05       0
Bank Sta=206.83,222.1
XS Rating Curve= 0 ,0
Exp/Cntr(USF)=0,0
Exp/Cntr=0.3,0.1

Type RM Length L Ch R = 1 ,3900    ,207.4,216.3,220.4
XS GIS Cut Line= 6
1658695.32256909492157.9756274221658644.71801151492229.568660095
1658601.69414742492291.1131564231658545.50331493492373.833463416
1658492.18025884492429.6056615861658422.02390309492489.016960084
#Sta/Elev= 30
       0 1077.57     5.5 1076.61    25.8 1074.45    71.6 1073.67   117.9 1066.32
   141.9 1061.09   148.3 1058.83   157.9 1054.26   165.9 1051.64   180.6 1048.52
   193.1 1046.75   197.7 1044.35     204 1039.53   205.7 1038.68   209.6 1037.71
     212 1037.65  218.181038.679   221.5 1039.75   227.3 1040.79   230.9 1042.03
     238  1043.2   277.9 1047.43   301.1  1050.7   319.4 1054.81   333.6 1058.53
   359.2 1065.34   378.4 1071.12   407.3 1078.09   419.7  1080.5   431.9 1084.48
#Mann= 4 ,-1,0
       0      .1       0  202.76     .05       0   205.7    .045       0
  218.18     .05       0
Bank Sta=205.7,218.18
XS Rating Curve= 0 ,0
Exp/Cntr(USF)=0,0
Exp/Cntr=0.3,0.1

Type RM Length L Ch R = 1 ,3684    ,233.7,234.3,233.8
XS GIS Cut Line= 3
1658654.37455181492169.8342906561658366.43254982 492197.97797857
1658277.65337382 492337.20064714
#Sta/Elev= 30
       0 1071.69    36.7 1066.85    46.5 1064.99    72.9 1058.29   122.4 1047.44
   142.1  1045.1     152  1045.2   161.9    1043   175.1 1041.07   204.8 1038.81
   208.1 1037.99   213.91034.968   221.3 1033.59   224.5 1033.74  228.621034.967
   234.4  1037.3   247.6 1038.33   260.8 1038.66   269.9 1040.64   277.3 1040.99
   284.9 1042.06   304.8 1045.92   328.9 1048.18   348.4 1051.15     364 1055.08
   383.3 1060.71   399.9 1066.93   418.9 1071.23   431.8 1075.27   454.4 1081.22
#Mann= 4 ,-1,0
       0      .1       0     110     .05       0   213.9    .045       0
  228.62     .05       0
Bank Sta=213.9,228.62
XS Rating Curve= 0 ,0
Exp/Cntr(USF)=0,0
Exp/Cntr=0.3,0.1

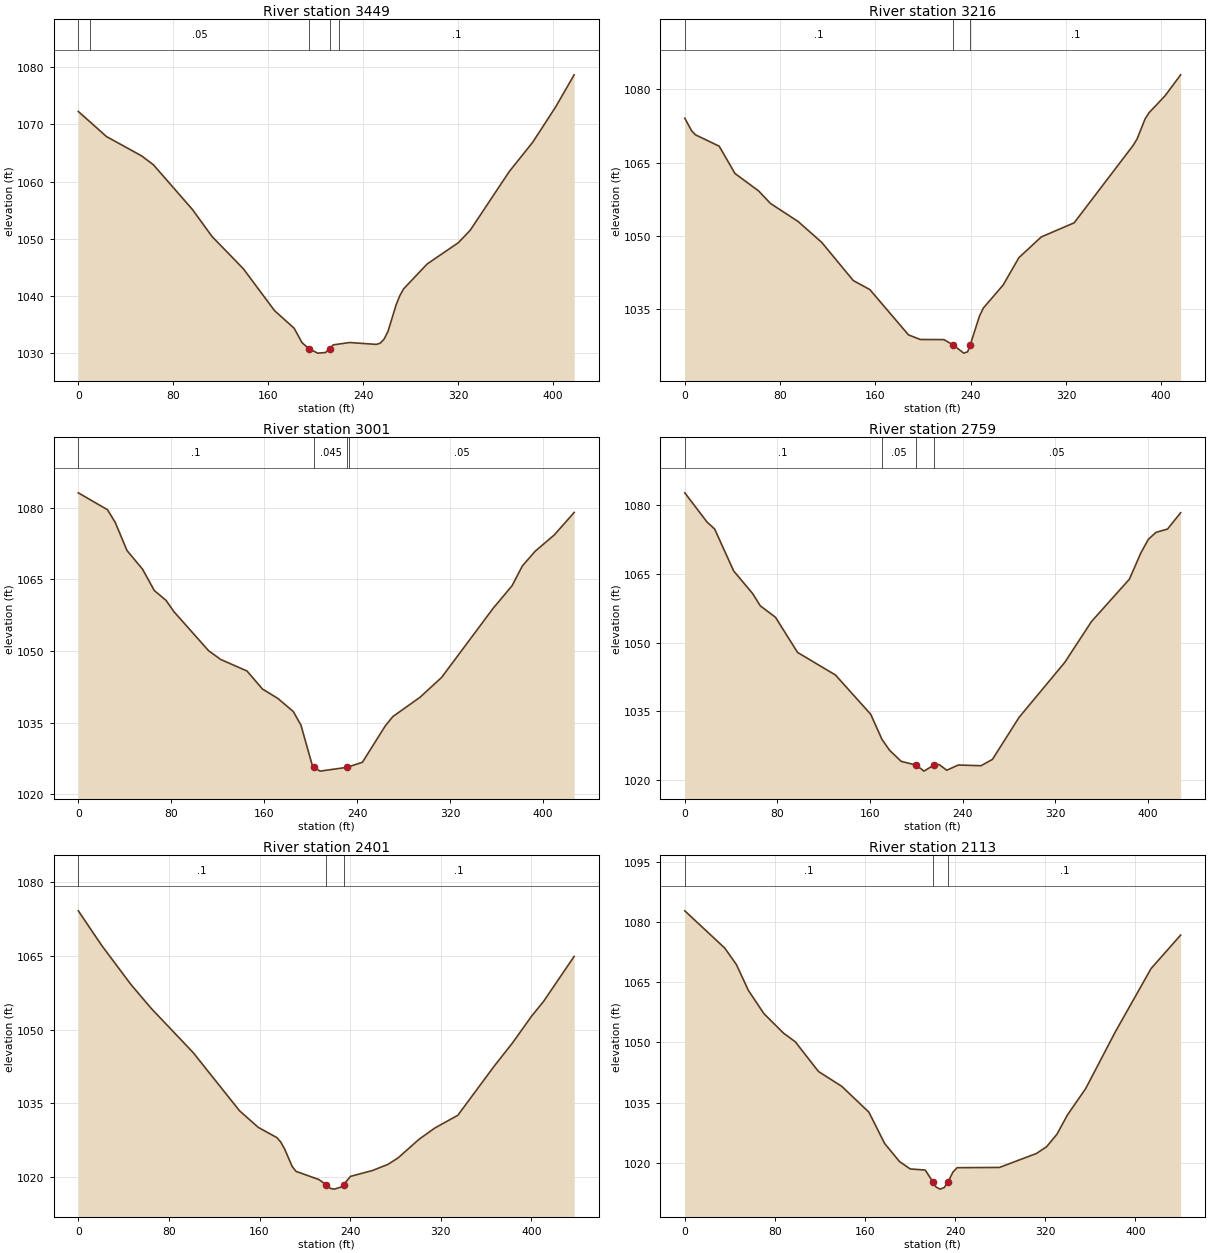
Type RM Length L Ch R = 1 ,3449    ,232.8,233.4,231.3
XS GIS Cut Line= 2
1658615.25838272 491943.180325681658199.22159012491982.992458944
#Sta/Elev= 30
       0 1072.28    23.7 1067.89    53.4 1064.49    63.3 1062.94    96.2  1055.1
   112.7 1050.37   139.1 1044.72   165.4 1037.38   181.9  1034.3   188.5 1031.79
  194.151030.743   201.7 1029.94   208.3 1030.04  211.971030.742   214.9 1031.39
   228.7  1031.8   251.1 1031.47   254.4 1031.68   257.7 1032.39     261 1033.75
   267.8 1038.37   270.9 1039.98   274.2 1041.21     294 1045.56   320.3 1049.29
   330.2 1051.44   363.2 1061.75     383  1066.9   402.2 1073.04   417.9  1078.7
#Mann= 5 ,-1,0
       0      .1       0      10     .05       0  194.15    .045       0
  211.97     .05       0     220      .1       0
Bank Sta=194.15,211.97
XS Rating Curve= 0 ,0
Exp/Cntr(USF)=0,0
Exp/Cntr=0.3,0.1

Type RM Length L Ch R = 1 ,3216    ,212.1,215.6,210.2
XS GIS Cut Line= 2
1658580.92029319491714.539450062 1658168.3365578491770.300300755
#Sta/Elev= 30
       0 1074.06     5.7 1071.51       9 1070.67    28.9 1068.35    42.1 1062.78
      62 1059.21    71.9 1056.66    95.1 1052.97     115 1048.69   141.5 1040.89
   155.4 1039.05   187.8  1029.8   197.7 1028.86   217.6 1028.83  225.181027.768
   234.2 1026.07   237.5 1026.34  239.671027.765   247.4 1033.63   250.7 1035.29
   267.3 1039.99   280.5 1045.57   299.3 1049.81   326.9 1052.69   376.5 1068.53
   379.8 1069.86   386.4 1073.89   389.8 1075.18   403.3 1078.67   416.3 1082.93
#Mann= 3 ,-1,0
       0      .1       0  225.18    .045       0  239.67      .1       0
Bank Sta=225.18,239.67
XS Rating Curve= 0 ,0
Exp/Cntr(USF)=0,0
Exp/Cntr=0.3,0.1

Type RM Length L Ch R = 1 ,3001    ,240.2,241.4,243.2
XS GIS Cut Line= 6
1658566.99999109491512.8407628391658481.24720985491531.455226928
1658406.97931376491542.0851269221658307.77085076491554.739957258
  1658232.590883491564.005358666 1658144.8174365491573.444972336
#Sta/Elev= 30
       0 1083.15    25.1 1079.61    31.8 1076.93    41.9 1071.05    55.3 1067.13
    65.4 1062.67    75.5 1060.61    82.2 1058.27   112.1 1050.06   122.6 1048.21
   145.2  1045.8   158.5 1042.02   171.7 1040.06     185 1037.31   191.6 1034.47
   201.5 1025.94  202.691025.612   208.1 1024.81  231.331025.611   244.5 1026.66
   264.3 1034.32   270.8 1036.26   294.1 1040.29   312.7 1044.45   356.9 1058.89
   373.4 1063.69   382.2 1067.82   393.2  1070.9   409.7 1074.32   426.8 1079.04
#Mann= 4 ,-1,0
       0      .1       0  202.69    .045       0  231.33      .1       0
  232.77     .05       0
Bank Sta=202.69,231.33
XS Rating Curve= 0 ,0
Exp/Cntr(USF)=0,0
Exp/Cntr=0.3,0.1

Type RM Length L Ch R = 1 ,2759    ,354.6,357.8,350.4
XS GIS Cut Line= 2
1658564.89074335491298.213248545  1658137.448935491321.744070125
#Sta/Elev= 30
       0  1082.6    19.2 1076.24    25.8 1074.71    42.2 1065.59    58.6 1060.66
    65.2 1057.99    78.3  1055.5    97.4 1047.84   130.1 1042.93   160.5 1034.39
   170.3 1028.89   176.9 1026.52   186.8 1024.14     2001023.288   206.5    1022
  214.85 1023.28   219.6 1023.44   226.2 1022.19   236.1 1023.33   255.8 1023.18
   265.6 1024.55   288.6  1033.7   328.1 1045.69   351.1 1054.56   383.9 1063.81
   393.8 1069.54   400.3 1072.49   406.9    1074   416.8 1074.71   428.1 1078.27
#Mann= 4 ,-1,0
       0      .1       0     170     .05       0     200    .045       0
  214.85     .05       0
Bank Sta=200,214.85
XS Rating Curve= 0 ,0
Exp/Cntr(USF)=0,0
Exp/Cntr=0.3,0.1

Type RM Length L Ch R = 1 ,2401    ,288.8,288.5,284.6
XS GIS Cut Line= 6
1658526.41345809490968.8950003391658436.83161625490989.476652086
 1658358.1752775491006.8224179151658258.42547701491031.818759009
1658186.75567284491053.9171400071658103.15971142491079.693991333
#Sta/Elev= 30
       0 1074.13    20.6 1067.11    46.3  1059.2    64.3 1054.32   101.4 1045.32
   142.4 1033.48   158.9 1030.12   175.4 1028.03   178.7 1027.15   182.1 1025.75
   188.8 1022.19   192.2 1021.18   212.5 1019.51  218.641018.473   222.6 1017.72
     226 1017.57   232.8 1018.05  234.171018.474   240.3 1020.16   259.8 1021.36
   273.4  1022.6   282.4 1023.93   300.8 1027.69   314.8 1029.99   335.1 1032.58
   367.3  1042.6   383.1  1047.2   400.4 1052.78   410.7 1055.69   437.8 1064.87
#Mann= 3 ,-1,0
       0      .1       0  218.64    .045       0  234.17      .1       0
Bank Sta=218.64,234.17
XS Rating Curve= 0 ,0
Exp/Cntr(USF)=0,0
Exp/Cntr=0.3,0.1

Type RM Length L Ch R = 1 ,2113    ,161.5,164,164
XS GIS Cut Line= 6
1658447.92345759490676.7364639191658360.06175667490707.872556508
1658281.84931467490732.7206039281658193.52239159490783.481329173
  1658139.768234490835.7833899261658068.54691976490887.469310179
#Sta/Elev= 30
       0 1082.77    35.5 1073.49    45.9 1069.35    56.4 1062.98    70.3 1057.15
    87.7  1052.3    98.1 1050.16   118.7 1042.76   139.4 1039.06   163.5 1032.61
   177.4 1024.84   190.6 1020.35   200.1  1018.5   213.5 1018.22  220.151015.314
   222.9 1014.04   226.6 1013.47   230.4 1013.88  233.831015.315     238 1017.69
   241.8 1018.81   279.4 1018.87   312.2 1022.35   321.3 1024.05   330.5 1027.18
   339.6 1031.89     356 1038.55   382.2 1052.62     414 1068.41   440.2 1076.73
#Mann= 3 ,-1,0
       0      .1       0  220.15    .045       0  233.83      .1       0
Bank Sta=220.15,233.83
XS Rating Curve= 0 ,0
Exp/Cntr(USF)=0,0
Exp/Cntr=0.3,0.1

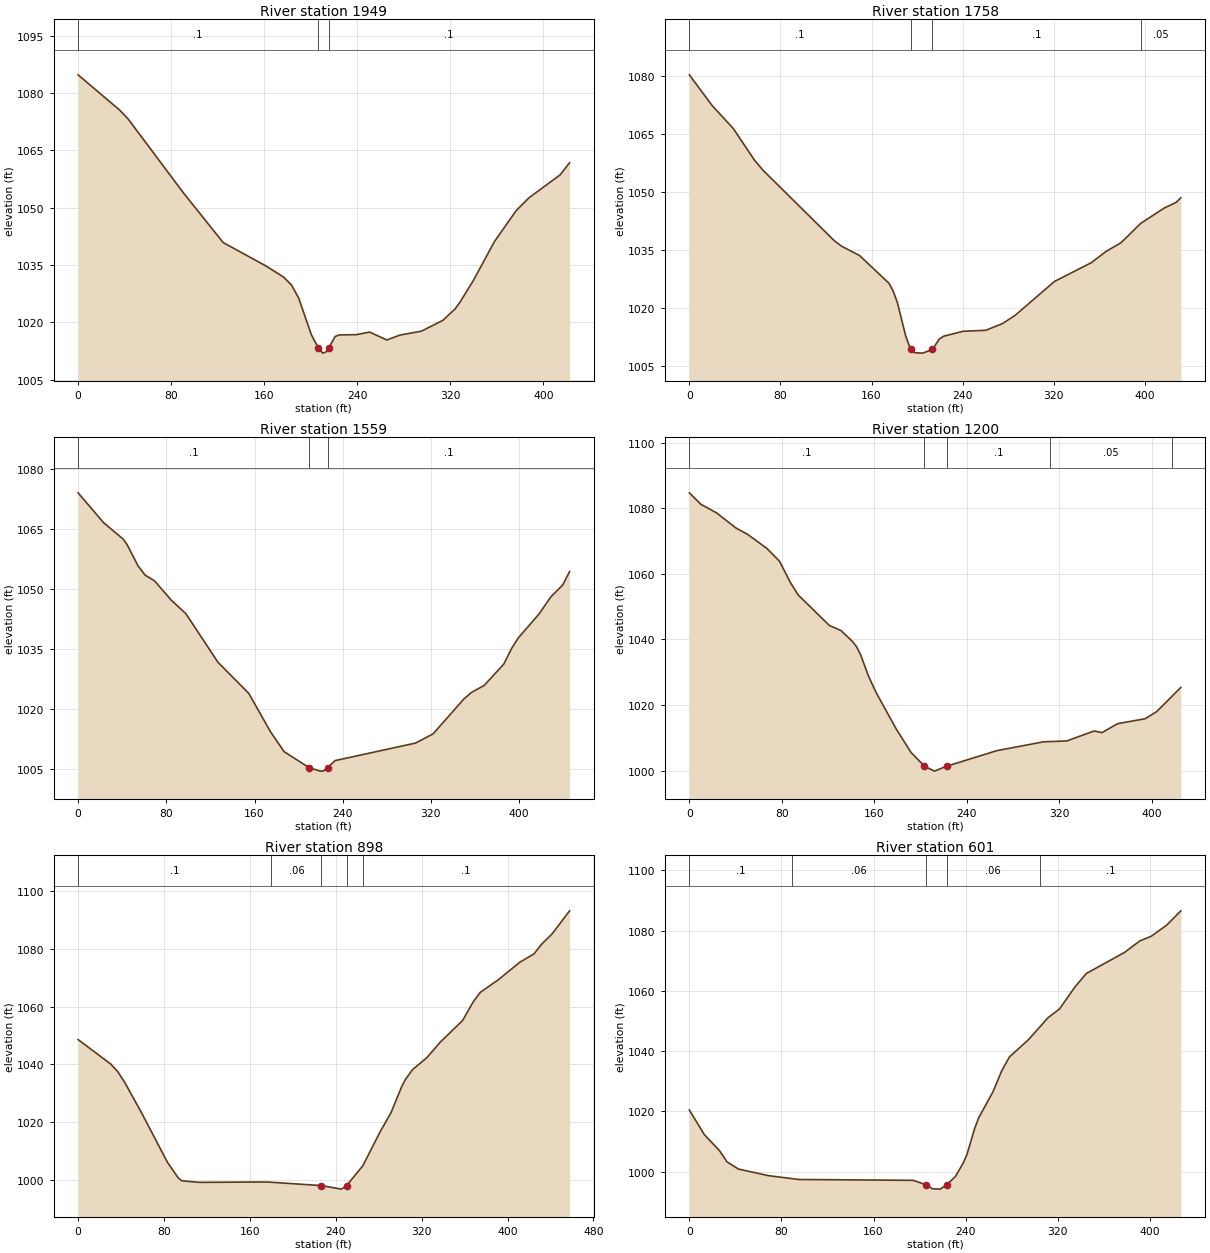
Type RM Length L Ch R = 1 ,1949    ,189.7,191.1,189.6
XS GIS Cut Line= 2
 1658400.2728631490535.8214147991658026.03881042490731.896171124
#Sta/Elev= 30
       0 1084.75    35.8 1075.51    43.2 1073.12    90.6 1053.85   124.7 1040.88
   161.7 1034.72   176.6 1031.86   183.5 1029.76   189.6 1026.36   200.5 1016.78
  206.541013.313   210.2 1011.96   213.6 1012.32   215.51013.313     221 1016.32
   224.7 1016.72   239.4 1016.79   250.6 1017.47   265.4  1015.4   276.6 1016.68
   295.1  1017.7   313.6 1020.54   323.9 1023.46   328.4 1025.34   339.5 1030.81
     358 1041.19   376.6 1049.23   387.8 1052.64   414.4  1058.6   422.5 1061.77
#Mann= 3 ,-1,0
       0      .1       0  206.54    .045       0   215.5      .1       0
Bank Sta=206.54,215.5
XS Rating Curve= 0 ,0
Exp/Cntr(USF)=0,0
Exp/Cntr=0.3,0.1

Type RM Length L Ch R = 1 ,1758    ,198.4,199,199.6
XS GIS Cut Line= 3
1658307.59334847490375.300354222 1658053.0098158490507.477441848
1657915.00644091490551.017178012
#Sta/Elev= 30
       0 1080.28      20 1072.34    38.5 1066.43      57 1058.31    64.4 1055.71
   126.9 1037.53   133.5 1036.03   149.4 1033.61   175.3 1026.43     179 1024.42
   182.7  1021.4   190.1 1012.69   194.31009.325   197.5  1008.5   204.9 1008.38
  213.381009.324   219.6 1012.05   223.3 1012.75   240.3 1014.02   260.3 1014.28
   275.1 1016.03   286.2 1018.17   320.6 1026.89     353 1031.75     366 1034.67
   379.1  1036.9   396.3 1041.89     417 1045.86   427.3 1047.29   431.6 1048.52
#Mann= 4 ,-1,0
       0      .1       0   194.3    .045       0  213.38      .1       0
  396.85     .05       0
Bank Sta=194.3,213.38
XS Rating Curve= 0 ,0
Exp/Cntr(USF)=0,0
Exp/Cntr=0.3,0.1

Type RM Length L Ch R = 1 ,1559    ,355.8,358.6,358.5
XS GIS Cut Line= 2
1658222.49735928490216.4100019021657811.53415457490389.235267095
#Sta/Elev= 30
       0 1074.07    23.1 1066.62    40.9  1062.5    44.4 1061.15    54.3 1055.84
    60.7 1053.53    69.3 1052.09    84.3 1047.31    97.8 1043.86   126.9 1031.72
   154.8 1023.96   174.5 1014.38   186.8 1009.41  209.381005.426   219.6 1004.53
   222.4 1004.55  226.351005.426   233.1 1007.16   306.2 1011.55     322 1013.84
   349.9 1022.56   356.9 1024.21   368.3 1025.93   386.1 1031.27   393.2 1035.17
   399.2 1037.79   418.1  1043.8   428.8 1048.07   439.5 1051.02   445.8  1054.4
#Mann= 3 ,-1,0
       0      .1       0  209.38    .045       0  226.35      .1       0
Bank Sta=209.38,226.35
XS Rating Curve= 0 ,0
Exp/Cntr(USF)=0,0
Exp/Cntr=0.3,0.1

Type RM Length L Ch R = 1 ,1200    ,289.7,301.6,300.3
XS GIS Cut Line= 6
1658165.03754042489926.4328464271658079.83725151489946.177557588
1658006.80688576 489963.102392511657909.38319609489985.680103257
1657836.23767309490002.4474581781657751.49965359490025.303383589
#Sta/Elev= 30
       0 1084.74      10 1081.23    23.5 1078.64    40.3 1074.01    50.4 1072.07
    67.1 1067.76      78 1063.87    87.5  1057.3    94.2 1053.55   121.1 1044.27
   131.2 1042.71   141.3 1039.32   144.7 1037.72   148.1 1035.39   154.8 1028.96
   161.5 1023.84   179.2 1012.52   191.8  1005.5  203.42  1001.3   212.1  999.81
  222.53  1001.3   265.9 1006.05   306.3 1008.75   326.5 1009.02   350.2 1012.06
     357 1011.57   370.6  1014.3   394.4 1015.81   404.3 1017.97   425.2 1025.36
#Mann= 5 ,-1,0
       0      .1       0  203.42    .045       0  222.53      .1       0
  312.43     .05       0  417.47     .06       0
Bank Sta=203.42,222.53
XS Rating Curve= 0 ,0
Exp/Cntr(USF)=0,0
Exp/Cntr=0.3,0.1

Type RM Length L Ch R = 1 ,898     ,301.2,297.7,295.1
XS GIS Cut Line= 5
1658063.94417714489758.3245980481657870.54337876489732.699966177
  1657771.095743489721.4093063321657697.12509042489708.516615584
1657610.92283501489693.081607088
#Sta/Elev= 30
       0  1048.6    30.3 1040.18    36.9 1037.54    43.5 1033.76    59.5 1023.01
    83.2 1006.22    93.2 1000.83    96.5   999.8     113  999.26   175.9  999.39
  226.62998.1458   245.3  996.92  250.04 998.146   265.1 1004.94   281.6 1016.91
   291.5 1023.36   301.5 1032.43   304.8 1034.78   311.5 1038.23   324.8 1042.34
   337.3 1047.71   358.1 1055.18   368.1 1061.69   374.7 1064.96   391.1 1069.19
   411.4 1075.34   424.7 1078.24   431.4 1081.44   441.4  1085.1   457.8 1093.11
#Mann= 5 ,-1,0
       0      .1       0     180     .06       0  226.62    .045       0
  250.04     .06       0  265.09      .1       0
Bank Sta=226.62,250.04
XS Rating Curve= 0 ,0
Exp/Cntr(USF)=0,0
Exp/Cntr=0.3,0.1

Type RM Length L Ch R = 1 ,601     ,132.3,136.3,140.4
XS GIS Cut Line= 6
1658040.38129367489415.4397739171657951.56519835489415.213724509
1657876.40393133489422.4066235131657778.32341884489441.957437426
1657704.79699109489456.7635101681657618.02419876 489468.76807934
#Sta/Elev= 30
       0 1020.43      13 1012.29    26.2 1006.96    32.7 1003.24    42.6 1000.85
    68.8  998.66    95.1  997.39   194.4  997.11  205.74995.6355   211.1  994.31
   217.8  994.19  223.56995.6338   231.2  998.44   237.9 1002.87   241.2 1005.79
   247.9 1014.43   251.4 1017.93   263.8 1026.55   271.3 1033.44     278 1038.06
   294.8 1043.88   311.5 1051.07   321.5 1053.98   334.9 1061.28   344.9 1065.78
     378 1072.75   391.3 1076.57   401.2 1078.12   414.5 1081.76   426.9 1086.55
#Mann= 5 ,-1,0
       0      .1       0   88.82     .06       0  205.74    .045       0
  223.56     .06       0  304.33      .1       0
Bank Sta=205.74,223.56
XS Rating Curve= 0 ,0
Exp/Cntr(USF)=0,0
Exp/Cntr=0.3,0.1

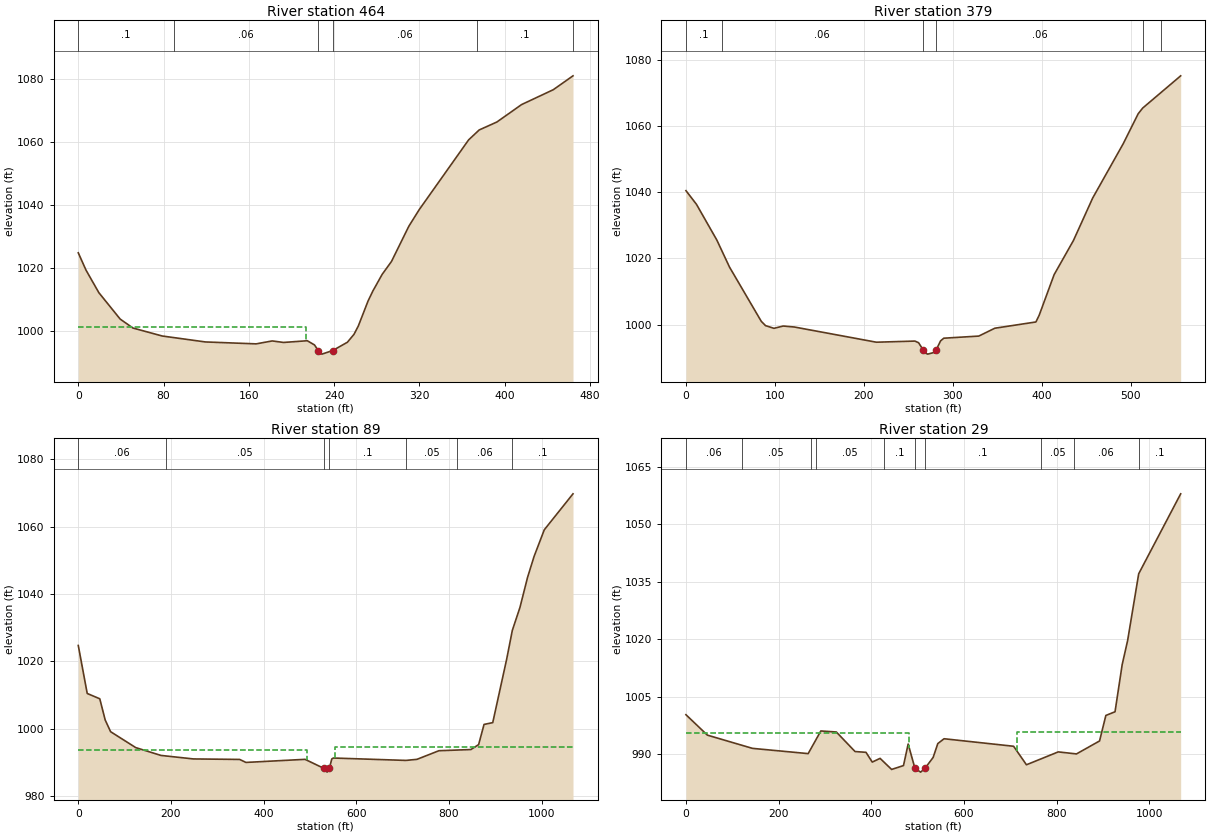
Type RM Length L Ch R = 1 ,464     ,83.5,84.9,85.7
XS GIS Cut Line= 4
1658046.49694592489412.1609950991657909.40648645489317.041340053
1657787.53050272  489281.29178471657618.57713914489303.116783048
#Sta/Elev= 30
       0 1024.89     7.3 1019.38    19.3 1012.27    39.3  1003.9    51.3 1001.06
    78.8  998.53   119.3  996.65   166.9  996.04     182  996.97   192.6  996.49
   214.9  997.03   221.7  995.69  225.09993.9313   228.6  992.79  238.75993.9313
   252.5  996.55   258.7  999.06   262.8 1001.73   271.9 1009.62   276.4 1012.78
   285.1 1018.04   293.9 1022.16   310.1 1033.27     320 1038.62   366.3 1060.69
   376.2 1063.82   392.8 1066.34   415.9 1071.85   445.7 1076.57   464.2 1080.97
#Mann= 6 ,-1,0
       0      .1       0      90     .06       0  225.09    .045       0
  238.75     .06       0  373.87      .1       0  463.87     .05       0
#XS Ineff= 2 , 0
          213.72 1001.45
Permanent Ineff=
       F       F
Bank Sta=225.09,238.75
XS Rating Curve= 0 ,0
Exp/Cntr(USF)=0,0
Exp/Cntr=0.3,0.1

Type RM Length L Ch R = 1 ,379     ,290.3,290.8,288.8
XS GIS Cut Line= 4
1658096.41856392489349.1891828281657932.29517445489247.925680056
1657757.58210028489170.3979601661657596.00135397489230.314814414
#Sta/Elev= 30
       0 1040.48    11.8 1036.36    34.7 1025.58      49 1017.39    84.7 1001.02
    89.5  999.72      99  998.91   109.3   999.6   121.8  999.31   214.1  994.72
   257.5  995.06   261.6  994.56  266.44992.5125   268.3  991.53   271.9  991.12
   279.1  991.63  281.55992.5112   286.3  995.11   289.9  995.93   329.3  996.57
   347.3  998.94   393.5 1000.83   397.2 1002.87     414 1015.12   435.7 1025.42
   457.4 1038.27   491.7 1054.65   508.5 1063.69   513.6 1065.42   556.3 1075.15
#Mann= 6 ,-1,0
       0      .1       0      40     .06       0  266.44    .045       0
  281.55     .06       0  513.99      .1       0  533.99     .05       0
Bank Sta=266.44,281.55
XS Rating Curve= 0 ,0
Exp/Cntr(USF)=0,0
Exp/Cntr=0.3,0.1

Type RM Length L Ch R = 1 ,89      ,56.7,59.6,55.1
XS GIS Cut Line= 4
1658327.73116924489278.5296801421658167.99112837 489026.63192338
1657769.86979573488933.2454379461657478.65141352489145.822569262
#Sta/Elev= 30
       0 1024.68    19.3 1010.42    46.4 1008.84    58.1 1002.54    69.8  999.06
   124.1  994.33   178.5  992.01   248.5  990.97   348.4  990.82   361.9  989.93
   489.5  990.85  529.48988.2092   537.1  987.05  542.05 988.211   547.2  990.96
   550.6  991.24   707.2  990.53   731.1  990.85   778.4  993.41   847.4  993.76
   864.1  995.22   875.8 1001.22   894.6 1001.76   924.6 1020.58   936.8 1029.13
   953.3 1035.97   969.7  1044.9   983.8 1051.13  1005.8 1059.04  1067.8 1069.73
#Mann= 7 ,-1,0
       0     .06       0     190     .05       0  529.48    .045       0
  542.05      .1       0   707.2     .05       0   817.2     .06       0
   937.2      .1       0
#XS Ineff= 2 , 0
          494.73  993.55  553.65          994.53
Permanent Ineff=
       F       F
Bank Sta=529.48,542.05
XS Rating Curve= 0 ,0
Exp/Cntr(USF)=0,0
Exp/Cntr=0.3,0.1

Type RM Length L Ch R = 1 ,29      ,,,
XS GIS Cut Line= 4
1658311.14278038489222.6206658361658151.40273951488970.722909074
1657753.28140687 488877.336423641657462.06302466489089.913554957
#Sta/Elev= 30
       0 1000.34    46.3  995.01   143.6  991.56   263.8  990.19   291.1   996.1
   324.6  995.83     365  990.73   388.6  990.53   402.1  987.98     419  988.95
   443.9  986.06   469.5  987.07   479.6  992.69  494.33  986.31   506.6  985.36
  515.73986.3264   533.5  989.19   543.6  992.81   557.1  994.07   707.2  992.11
   734.9  987.28   803.6  990.64   842.9  990.11   892.7  993.49   906.3 1000.15
   926.1 1001.11   941.5 1013.39   953.3  1019.7   977.2 1037.12  1067.8 1057.98
#Mann= 10 ,-1,0
       0     .06       0     120     .05       0     270      .1       0
     280     .05       0  428.28      .1       0  494.33    .045       0
  515.73      .1       0   767.2     .05       0   837.2     .06       0
   977.2      .1       0
#XS Ineff= 2 , 0
          481.73  995.53   714.8          995.87
Permanent Ineff=
       F       F
Bank Sta=494.33,515.73
XS Rating Curve= 0 ,0
Exp/Cntr(USF)=0,0
Exp/Cntr=0.3,0.1
LCMann Table=0

Chan Stop Cuts=-1
Use User Specified Reach Order=0
Composite Channel Slope=5